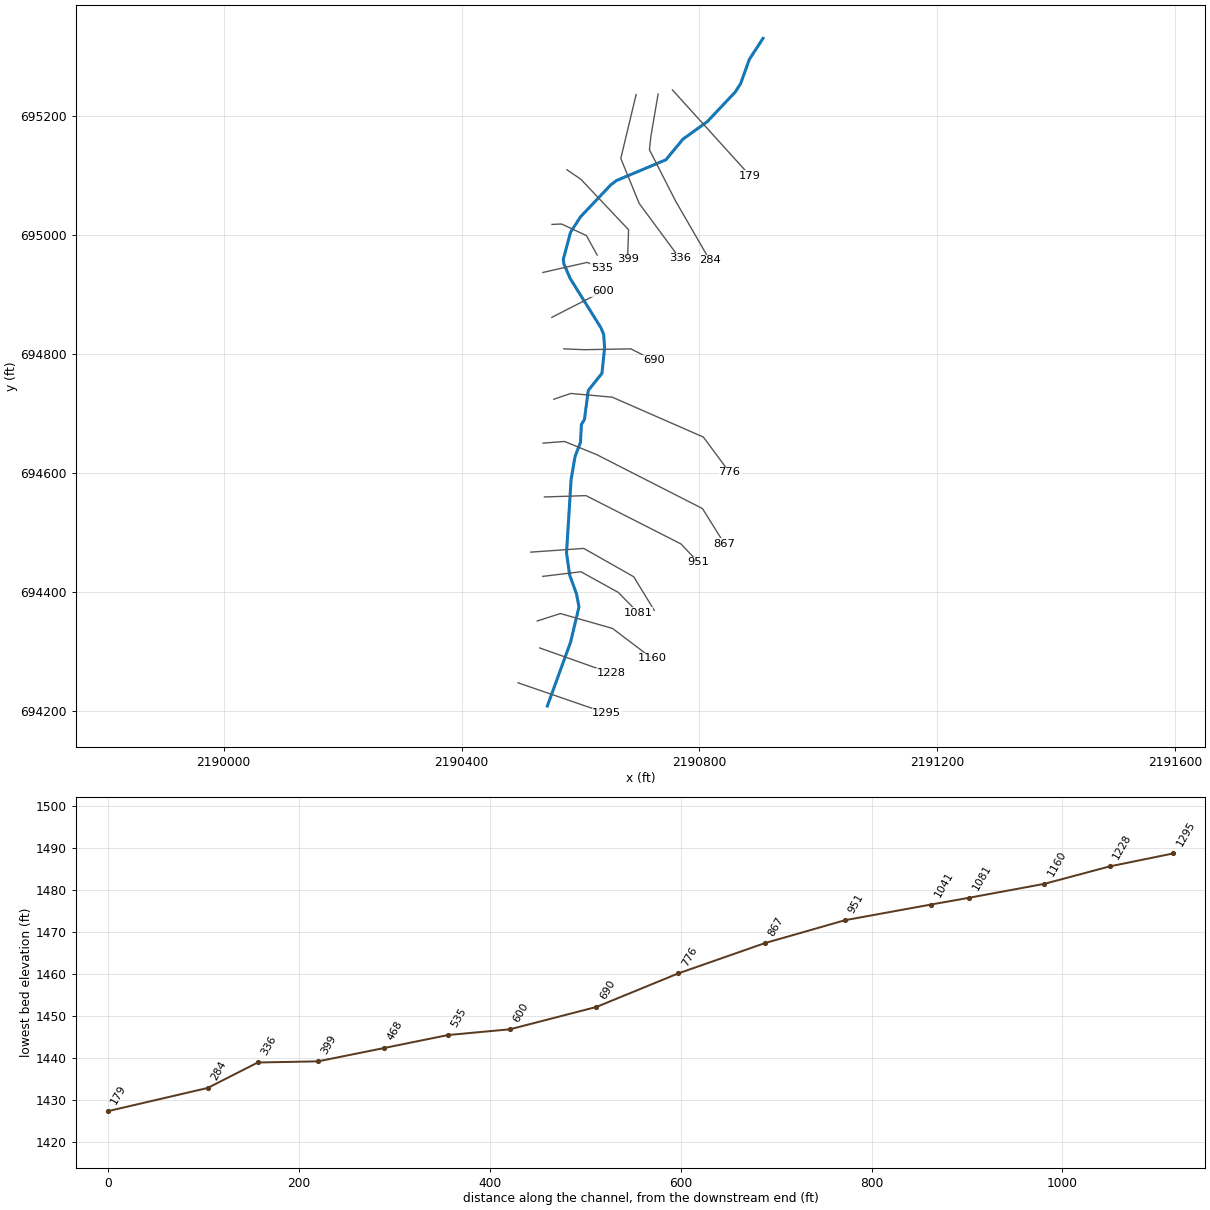
--- SAWMILLRN.prj (project) ---

Proj Title=SAWMILLRN
Current Plan=p01
Default Exp/Contr=0,0
English Units
Geom File=g01
Flow File=f01
Plan File=p01
BEGIN DESCRIPTION:
---------- MODELED AS PART OF WVEMD CTP PROGRAM, 2023----------
Stream Name: Sawmill Run
Flood Zone:  AFH
Upshur County, WV
HEC-RAS Version: RAS 6.3
Vertical Datum: NAVD88
Projection: NAD 1983 StatePlane West Virginia S FIPS 4702 (US Feet)
Terrain: 1-meter LIDAR (FEMA Region III 3DEP collected 2016-2018)
Land Use: 2019 NLCD
Hydrologic Method:
WV SIR2010-5033 regression equations
Additional Model Notes:
None
END DESCRIPTION:
DSS Export Rating Curves= 0
DSS Export Rating Curve Sorted= 0
DSS Export Volume Flow Curves= 0
DXF OffsetX= 0
DXF OffsetY= 0
DXF ScaleX= 0
DXF ScaleY= 0

--- SAWMILLRN.p01 (plan) ---

Plan Title=Floodplain
Program Version=6.30
Short Identifier=Floodplain
Geom File=g01
Flow File=f01
Subcritical Flow
K Sum by GR= 0
Std Step Tol= 0.01
Critical Tol= 0.01
Num of Std Step Trials= 20
Max Error Tol= 0.3
Flow Tol Ratio= 0.001
Split Flow NTrial= 30
Split Flow Tol= 0.02
Split Flow Ratio= 0.02
Log Output Level= 0
Friction Slope Method= 1
Unsteady Friction Slope Method= 2
Unsteady Bridges Friction Slope Method= 1
Parabolic Critical Depth
Global Vel Dist= 0 , 0 , 0
Global Log Level= 0
CheckData=False
Encroach Param=-1 ,0,0, 0
Mapping Interval=1HOUR
Computation Time Step Use Courant=        0
Computation Time Step Use Time Series=    0
Computation Time Step Count To Double=0
Computation Time Step Max Doubling=0
Computation Time Step Max Halving=0
Computation Time Step Residence Courant=0
Run HTab= 0
Run UNet= 0
Run Sediment= 0
Run PostProcess= 0
Run WQNet= 0
Run RASMapper=-1
UNET Theta= 0
UNET Theta Warmup= 0
UNET ZTol= 0
UNET ZSATol= 0
UNET MxIter= 0
UNET Max Iter WO Improvement= 0
UNET MaxInSteps= 0
UNET DtIC= 0
UNET DtMin= 0
UNET MaxCRTS= 0
UNET WFStab= 0
UNET SFStab= 0
UNET WFX= 1
UNET SFX= 1
UNET Gravity=32.17405
UNET 1D Methodology=Finite Difference
UNET DSS MLevel= 1
UNET Pardiso=0
UNET DZMax Abort= 0
UNET Use Existing IB Tables= 0
UNET Froude Reduction=False
UNET Froude Limit= 0
UNET Froude Power= 0
UNET D1 Cores= 0
UNET WindReference=Eulerian
UNET WindDragFormulation=Hsu (1988)
UNET D2 Coriolis=0
UNET D2 Cores= 0
UNET D2 Theta= 1
UNET D2 Theta Warmup= 1
UNET D2 Z Tol= 0.01
UNET D2 Volume Tol= 0.01
UNET D2 Max Iterations= 20
UNET D2 Equation= 0
UNET D2 RampUpFraction=0.1
UNET D2 TimeSlices= 1
UNET D2 Turbulence Formulation=Non-Conservative (original)
UNET D2 Eddy Viscosity=0.3
UNET D2 Transverse Eddy Viscosity=0.1
UNET D2 Smagorinsky Mixing=0
UNET D2 BCVolumeCheck=0
UNET D2 Cores=0
UNET D2 SolverType=PARDISO (Direct)
UNET D2 Minimum Iterations= 3
UNET D2 Maximum Iterations= 30
UNET D2 Restart Number= 10
UNET D2 Relaxation Coeff=1.3
UNET D2 SOR Precondition Iterations= 10
UNET D2 ILUT Maximum Fill= 8
UNET D2 ILUT Tolerance=1E-08
UNET D2 Convergence Tolerance=0.00001
UNET D1D2 MaxIter= 0
UNET D1D2 ZTol=0.01
UNET D1D2 QTol=0.1
UNET D1D2 MinQTol=1
Write IC File= 0
Write IC File at Fixed DateTime=0
Write IC File at Sim End=0
Echo Input=False
Echo Parameters=False
Echo Output=False
Write Detailed= 0
HDF Write Warmup=0
HDF Write Time Slices=0
HDF Flush=0
HDF Compression= 1
HDF Chunk Size= 1
HDF Spatial Parts= 1
HDF Use Max Rows=0
HDF Fixed Rows= 1
Calibration Method= 0
Calibration Iterations= 20
Calibration Max Change=0.05
Calibration Tolerance=0.2
Calibration Maximum=1.5
Calibration Minimum=0.5
Calibration Optimization Method= 1
WQ AD Non Conservative
WQ ULTIMATE=-1
WQ Max Comp Step=1HOUR
WQ Output Interval=15MIN
WQ Output Selected Increments= 0
WQ Output face flow=0
WQ Output face velocity=0
WQ Output face area=0
WQ Output face dispersion=0
WQ Output cell volume=0
WQ Output cell surface area=0
WQ Output cell continuity=0
WQ Output cumulative cell continuity=0
WQ Output face conc=0
WQ Output face dconc_dx=0
WQ Output face courant=0
WQ Output face peclet=0
WQ Output face adv mass=0
WQ Output face disp mass=0
WQ Output cell mass=0
WQ Output cell source sink temp=0
WQ Output nsm pathways=0
WQ Output nsm derived pathways=0
WQ Create Restart=0
WQ Fixed Restart=0
WQ System Summary=0
WQ Write To DSS=0
Sorting and Armoring Iterations= 10
XS Update Threshold= 0.02
Bed Roughness Predictor= 0
Hydraulics Update Threshold= 0.02
Energy Slope Method= 1
Volume Change Method= 1
Sediment Retention Method= 0
Sediment TS Multiplier= 1
Warm Up Method= 0
XS Weighting Method= 0
Number of US Weighted Cross Sections= 1
Number of DS Weighted Cross Sections= 1
Upstream XS Weight=0
Main XS Weight=1
Downstream XS Weight=0
Number of DS XS's Weighted with US Boundary= 1
Upstream Boundary Weight= 1
Weight of XSs Associated with US Boundary= 0
Number of US XS's Weighted with DS Boundary= 1
Downstream Boundary Weight= 0.5
Weight of XSs Associated with DS Boundary= 0.5
Percentile Method= 0
Sediment Output Level= 3
Mass or Volume Output= 0
Output Increment Type= 1
Profile and TS Output Increment= 1
Transport Output Increment 1
XS Output Flag= 0
XS Output Increment= 10
Read HDF5 Sediment Hotstart= 0
Sediment Hotstart Type= 0
Write Gradation File= 0
Read Gradation Hotstart= 0
Write HDF5 File= 1
Write Binary Output= 1
Write DSS Sediment File= 0
DSS Sediment Output Type= 1
SV Curve= 0
Specific Gage Flag= 0
Subcell Erosion Methods= 0
Subcell Deposition Methods= 0
Advection Scheme= 1
Matrix Solver= 0
Implicit Weighting Factor= 1
Maximum Outer Loop Convergence Iterations= 5
Convergence Maximum Absolute= 0.001
Convergence RMSE= 0.0001
Grain Fractions Max Abs Error= 0.001
Max Subgrid Regions= 1
Max Subgrid Length Scale= 3.402823E+38
Initial Layer Thickness= 3.402823E+38
Min Layer Thickness= 3.402823E+38
Max Layer Thickness= 3.402823E+38
Number of Layers= 5

--- SAWMILLRN.f01 (steady flow) ---

Flow Title=Flows
Program Version=6.31
Number of Profiles= 1
Profile Names=01pct
River Rch & RM=SAWMILLRN,Main            ,1295
     345
Boundary for River Rch & Prof#=SAWMILLRN,Main            , 1
Up Type= 0
Dn Type= 3
Dn Slope=0.05303
DSS Import GetInterval= 0
DSS Import GetPeak= 0
DSS Import FillOption= 0

--- SAWMILLRN.g01 (geometry) ---

Geom Title=Geometry
Program Version=6.30

River Reach=SAWMILLRN       ,Main
Reach XY= 30
     2190544.194       694207.58     2190583.313      694314.978
      2190597.45      694374.443     2190593.071      694396.878
     2190581.854      694427.612     2190576.502      694465.156
       2190584.2      694588.808     2190590.954      694627.526
     2190599.968      694651.077      2190601.57      694681.182
     2190606.635       694689.48     2190613.074      694738.357
      2190636.11      694767.031     2190640.546      694810.671
     2190638.943      694832.476     2190634.508      694843.379
     2190582.397      694926.996     2190571.895      694951.635
     2190571.065      694958.904     2190583.199      695004.146
     2190600.168      695030.416     2190651.048      695084.129
     2190660.749      695091.398     2190743.565      695126.138
     2190772.238      695160.849     2190813.131      695190.267
     2190860.034      695239.917     2190869.219      695254.168
     2190883.928       695295.06     2190906.936      695330.402

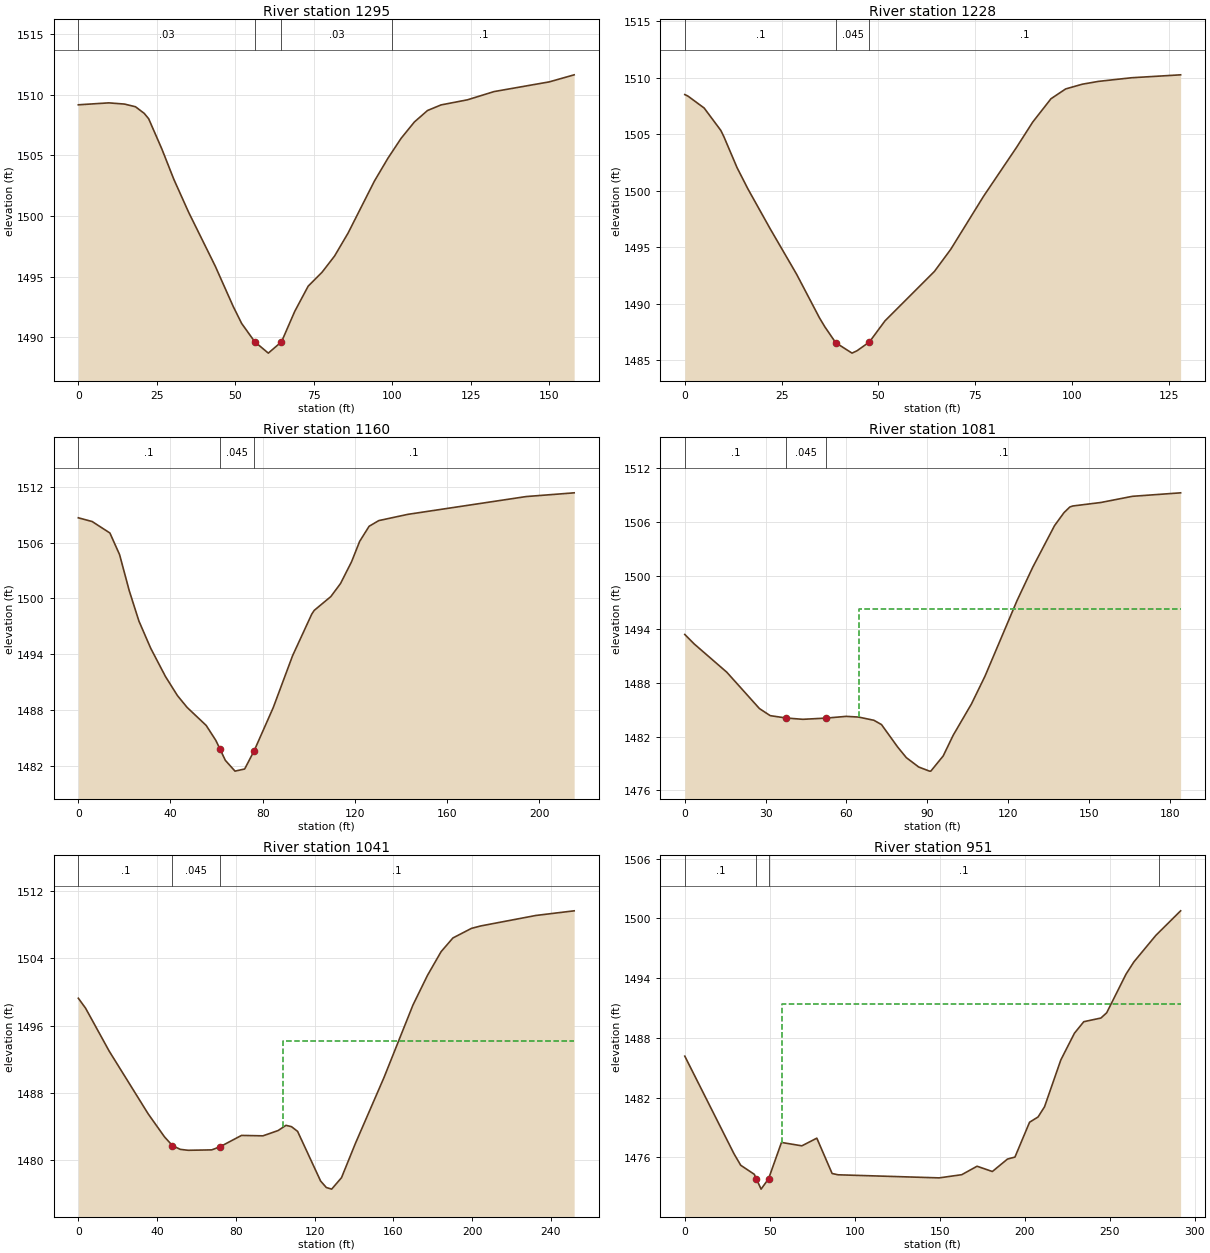
Type RM Length L Ch R = 1 ,1295    ,66.9,66.9,66.9
XS GIS Cut Line= 2
2190494.99167351694246.6836779222190644.25147515694195.285674603
#Sta/Elev= 30
       0 1509.17     9.7 1509.33    14.7 1509.23    18.2 1509.01      21 1508.46
    22.4 1508.02    26.6 1505.53    30.4 1503.04    35.1 1500.33    43.6 1495.88
    49.3 1492.57      52 1491.16    56.2 1489.64    60.5 1488.71    64.7 1489.64
    68.9 1492.14    73.2 1494.23    77.6 1495.37    81.6 1496.71    85.9  1498.6
    94.3 1502.89    98.6 1504.77   102.8 1506.41     107 1507.75   111.2  1508.7
   115.5 1509.16   123.9 1509.58   132.4 1510.26     150 1511.06   157.9 1511.64
#Mann= 4 ,-1,0
       0     .03       0    56.2    .045       0    64.7     .03       0
     100      .1       0
Bank Sta=56.2,64.7
XS Rating Curve= 0 ,0
Exp/Cntr(USF)=0,0
Exp/Cntr=0.3,0.1

Type RM Length L Ch R = 1 ,1228    ,68.2,68.2,68.2
XS GIS Cut Line= 2
2190531.42810201694305.2918508142190652.13232929694262.424928979
#Sta/Elev= 27
       0 1508.51      .8 1508.38       5 1507.32     9.3 1505.34    10.1 1504.78
    13.5 1502.04    16.3 1500.16      22 1496.66    28.9 1492.59    34.8 1488.73
    36.2 1487.93      39 1486.53    43.2 1485.61    44.5 1485.82    47.7  1486.6
    51.7 1488.46    64.5 1492.85    68.7  1494.8    77.2 1499.51    85.7 1503.83
    89.9 1506.08    94.6 1508.14    98.4 1509.01   102.7 1509.43   106.9 1509.68
   115.4    1510   128.1 1510.26
#Mann= 3 ,-1,0
       0      .1       0      39    .045       0    47.7      .1       0
Bank Sta=39,47.7
XS Rating Curve= 0 ,0
Exp/Cntr(USF)=0,0
Exp/Cntr=0.3,0.1

Type RM Length L Ch R = 1 ,1160    ,78.7,78.7,78.7
XS GIS Cut Line= 4
2190527.17850142 694350.623280782190566.17375195694363.157468451
2190653.91306565694338.089093108 2190720.0657228694287.952342424
#Sta/Elev= 30
       0 1508.65       6 1508.25    13.7 1507.02    17.9  1504.7    22.1 1500.83
    26.3 1497.57    31.4 1494.66    37.8 1491.63      43 1489.58    47.2 1488.31
    55.5 1486.37    59.7 1484.76    61.4 1483.88    63.8 1482.63      68 1481.47
    72.2  1481.7    76.3 1483.65    84.6 1488.29      93 1493.86   101.3 1498.31
   102.4 1498.72   109.6  1500.2   113.8  1501.6   118.6 1503.94   122.1 1506.12
   126.2 1507.74   130.4 1508.35     143 1509.02   194.4 1510.93   215.2 1511.33
#Mann= 3 ,-1,0
       0      .1       0    61.4    .045       0    76.3      .1       0
Bank Sta=61.4,76.3
XS Rating Curve= 0 ,0
Exp/Cntr(USF)=0,0
Exp/Cntr=0.3,0.1

Type RM Length L Ch R = 1 ,1081    ,39.9,39.9,39.9
XS GIS Cut Line= 4
2190536.66373248694425.6636338282190600.68508541 694433.43501193
2190663.59624148694398.6488432842190696.90214763694364.602805885
#Sta/Elev= 30
       0 1493.43     3.5 1492.37    15.6 1489.21    27.7 1485.15    31.7 1484.36
    37.61484.098    43.8 1483.95    52.51484.086    59.9 1484.28    64.5  1484.2
    70.2 1483.84      73 1483.36      79 1480.85    82.2 1479.67    86.8 1478.62
    90.8 1478.16    91.3 1478.16    95.9 1479.86    99.6 1482.17   106.4 1485.68
   111.4 1488.77   123.3 1497.22   129.1 1500.93   137.2 1505.59   140.7 1507.04
   142.9 1507.68     144 1507.79   154.4 1508.18   166.1 1508.87     184 1509.26
#Mann= 3 ,-1,0
       0      .1       0    37.6    .045       0    52.5      .1       0
#XS Ineff= 2 , 0
                           64.68         1496.33
Permanent Ineff=
       F       F
Bank Sta=37.6,52.5
XS Rating Curve= 0 ,0
Exp/Cntr(USF)=0,0
Exp/Cntr=0.3,0.1

Type RM Length L Ch R = 1 ,1041    ,90.3,90.3,90.3
XS GIS Cut Line= 4
2190516.49547337694466.4126836142190605.48820584694472.679777449
2190689.46726323694425.0498642992190723.93627933694368.646019779
#Sta/Elev= 30
       0 1499.26     3.7 1498.07    15.7 1492.96    35.5  1485.5    43.8 1482.76
    47.8 1481.73    51.8 1481.28    55.8 1481.17    67.8 1481.22    71.9 1481.58
    82.9 1482.94    93.8 1482.89   101.5 1483.52   105.5 1484.14   108.3 1483.98
   111.4 1483.42   123.1 1477.51     126 1476.74   128.7 1476.55   133.7 1477.91
   140.7 1481.95   155.4 1489.89     170 1498.45   177.4 1501.99   184.3  1504.8
   190.3 1506.43   199.7 1507.57   204.4 1507.86   232.5 1509.11   251.9 1509.66
#Mann= 3 ,-1,0
       0      .1       0    47.8    .045       0    71.9      .1       0
#XS Ineff= 2 , 0
                          103.94         1494.21
Permanent Ineff=
       F       F
Bank Sta=47.8,71.9
XS Rating Curve= 0 ,0
Exp/Cntr(USF)=0,0
Exp/Cntr=0.3,0.1

Type RM Length L Ch R = 1 ,951     ,84,84,84
XS GIS Cut Line= 4
2190539.32288585694559.1932990382190609.26365305694561.449452819
2190768.88653305 694480.22791671 2190798.2165322694449.205802223
#Sta/Elev= 30
       0 1486.17    28.9 1476.38    32.9 1475.21    40.9  1474.3   42.09 1473.85
    44.9 1472.81    49.3 1473.85    56.9  1477.5    68.9 1477.16    77.7 1477.93
    86.7 1474.38    90.2 1474.25   149.7 1473.94     163 1474.26     172 1475.11
     181 1474.58   189.9 1475.83   194.3 1476.03   202.9 1479.53   207.9 1480.06
   211.7 1481.08   221.3 1485.79   229.3 1488.47   234.8 1489.63   244.9    1490
   248.3 1490.53   259.7 1494.42   264.3 1495.64   277.2  1498.3   291.8 1500.77
#Mann= 4 ,-1,0
       0      .1       0   42.09    .045       0    49.3      .1       0
  279.08     .07       0
#XS Ineff= 2 , 0
                           57.13         1491.37
Permanent Ineff=
       F       F
Bank Sta=42.09,49.3
XS Rating Curve= 0 ,0
Exp/Cntr(USF)=0,0
Exp/Cntr=0.3,0.1

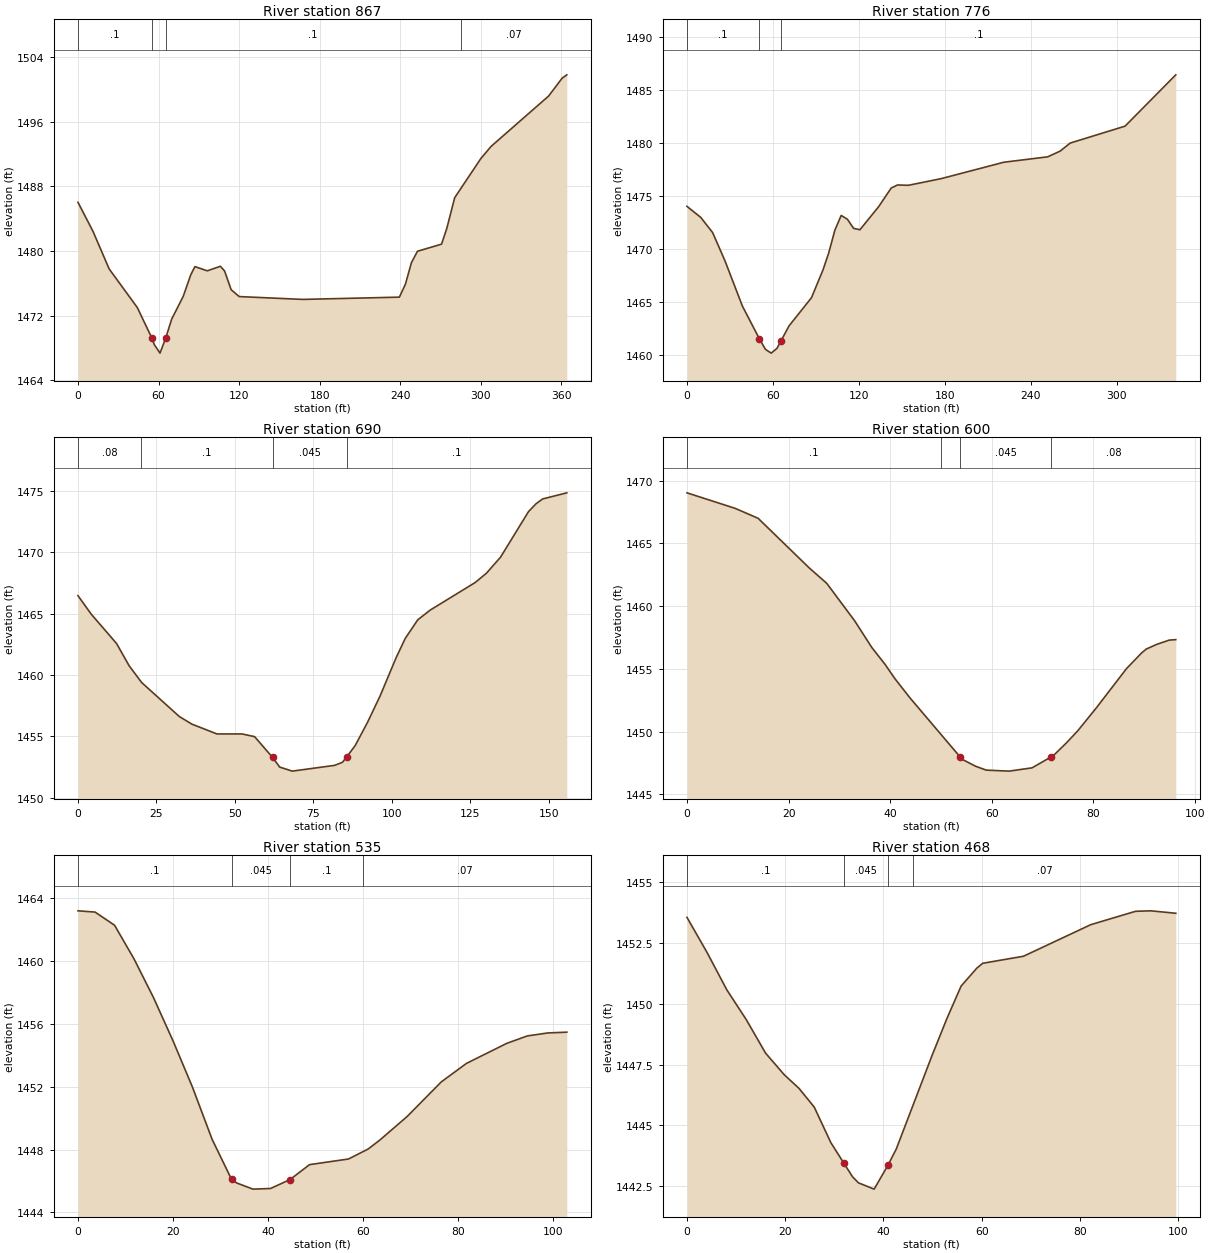
Type RM Length L Ch R = 1 ,867     ,90.6,90.6,90.6
XS GIS Cut Line= 5
 2190537.0252624694649.7138455092190573.23513789694652.499220547
2190627.54995114694630.2162202432190805.11760981694539.691531507
2190842.02382906694480.502311948
#Sta/Elev= 30
       0 1486.02    11.2 1482.42    23.2 1477.78    44.2 1472.99    54.91469.264
    56.8 1468.42    61.1 1467.35    65.4 1469.24    69.8 1471.56    78.4 1474.38
      84 1477.04    87.1 1478.06    96.3 1477.54   106.1  1478.1   109.2 1477.52
   114.1  1475.2   120.1 1474.35   167.4    1474   239.4 1474.28   243.9 1475.88
   248.4 1478.56   252.9 1479.96   270.8 1480.84   274.7 1482.77   280.6 1486.59
   300.1 1491.44   307.7 1492.94   350.6 1499.18   360.6 1501.38   364.1  1501.8
#Mann= 4 ,-1,0
       0      .1       0    54.9    .045       0    65.4      .1       0
  285.02     .07       0
Bank Sta=54.9,65.4
XS Rating Curve= 0 ,0
Exp/Cntr(USF)=0,0
Exp/Cntr=0.3,0.1

Type RM Length L Ch R = 1 ,776     ,85.7,85.7,85.7
XS GIS Cut Line= 5
2190555.13020015694723.5262840172190583.68029429 694733.27509665
2190653.31467024694727.0080028142190806.60104172694659.917335275
2190850.47069856694600.728115716
#Sta/Elev= 30
       0 1474.02     9.6 1472.98    17.9 1471.54    26.5 1468.88    38.7 1464.59
    50.61461.485    54.8  1460.5    58.8 1460.15    62.8  1460.6    65.61461.301
    71.2 1462.72    86.9 1465.39    94.9 1468.01    98.9 1469.61   103.2 1471.77
   107.6 1473.16   111.9 1472.81   116.3 1471.94   120.7 1471.81   133.8    1474
   142.5 1475.75   146.9 1476.04   154.5 1476.01   177.4 1476.64   221.1 1478.19
   251.7  1478.7   260.4 1479.24   267.4    1480   305.7  1481.6   341.1 1486.45
#Mann= 3 ,-1,0
       0      .1       0    50.6    .045       0    65.6      .1       0
Bank Sta=50.6,65.6
XS Rating Curve= 0 ,0
Exp/Cntr(USF)=0,0
Exp/Cntr=0.3,0.1

Type RM Length L Ch R = 1 ,690     ,90.6,90.6,90.6
XS GIS Cut Line= 4
2190571.93319476 694808.238556052190606.05403898694806.845868531
 2190684.7408838 694808.238556052190723.03979057694788.740930784
#Sta/Elev= 30
       0 1466.47     4.2 1464.97    12.3 1462.57    16.3 1460.76    20.3 1459.39
    32.3 1456.62    36.3    1456    44.3  1455.2    52.3  1455.2    56.3 1454.98
      621453.293    64.3  1452.5    68.3 1452.17    81.8 1452.64    84.3 1452.89
    85.7 1453.35    88.3 1454.23    92.3 1456.15    96.3  1458.3   101.4 1461.41
   104.3 1462.98   108.3  1464.5   112.3  1465.3   126.6 1467.54   130.2  1468.3
   134.7 1469.61   143.6 1473.32     146 1473.96   148.1 1474.35   155.8 1474.85
#Mann= 4 ,-1,0
       0     .08       0      20      .1       0      62    .045       0
    85.7      .1       0
Bank Sta=62,85.7
XS Rating Curve= 0 ,0
Exp/Cntr(USF)=0,0
Exp/Cntr=0.3,0.1

Type RM Length L Ch R = 1 ,600     ,64.9,64.9,64.9
XS GIS Cut Line= 2
2190551.73922574694861.1606817732190637.38950816694905.030338621
#Sta/Elev= 27
       0 1469.03     9.5 1467.79      14    1467    24.1 1463.03    27.5 1461.82
      33 1458.83    36.4 1456.69      39 1455.35    40.9 1454.23    43.9 1452.68
    53.8 1447.96    54.4 1447.74    56.8 1447.24    58.9 1446.93    63.4 1446.85
    67.9 1447.11    71.7 1447.99    72.4  1448.2    74.7 1449.11    76.9 1450.06
    80.6 1451.91    86.5 1455.02    89.5 1456.28    90.4 1456.58    92.5 1456.96
    94.9 1457.29    96.2 1457.33
#Mann= 4 ,-1,0
       0      .1       0      50     .08       0    53.8    .045       0
    71.7     .08       0
Bank Sta=53.8,71.7
XS Rating Curve= 0 ,0
Exp/Cntr(USF)=0,0
Exp/Cntr=0.3,0.1

Type RM Length L Ch R = 1 ,535     ,67.4,67.4,67.4
XS GIS Cut Line= 3
2190536.66058983694936.699794241 2190611.1136646694953.620947597
2190635.93135619694944.596332474
#Sta/Elev= 24
       0 1463.21     3.6 1463.13     7.7 1462.29    11.8 1460.14    15.9 1457.67
      20 1454.92    24.1 1451.96    28.2 1448.66    32.3  1446.1    33.4 1445.87
    36.8 1445.48    40.5 1445.52    44.6 1446.09    48.7 1447.04    56.9  1447.4
      61 1448.03    63.5 1448.61    69.2  1450.1    76.4 1452.31    81.7 1453.49
    90.2 1454.77    94.5 1455.24    98.8 1455.43   102.8 1455.48
#Mann= 4 ,-1,0
       0      .1       0    32.3    .045       0    44.6      .1       0
      60     .07       0
Bank Sta=32.3,44.6
XS Rating Curve= 0 ,0
Exp/Cntr(USF)=0,0
Exp/Cntr=0.3,0.1

Type RM Length L Ch R = 1 ,468     ,68.7,68.7,68.7
XS GIS Cut Line= 4
2190552.12716961695017.5130695992190568.14307608695018.209413359
2190609.92370165694998.711788093 2190628.0286394694965.983631396
#Sta/Elev= 25
       0 1453.56     4.1 1452.11     8.1 1450.58    12.1 1449.34      16 1447.97
    19.8 1447.08    22.8 1446.52    25.9 1445.75    29.3 1444.28    31.9 1443.45
    33.7 1442.88    34.9 1442.63    38.1 1442.37    40.9 1443.35    42.6 1444.02
    49.9 1447.88    52.9 1449.39    55.8 1450.73      59 1451.47    60.2 1451.67
    68.5 1451.96    82.2 1453.26    91.3 1453.81    94.4 1453.83    99.5 1453.73
#Mann= 4 ,-1,0
       0      .1       0    31.9    .045       0    40.9      .1       0
   46.03     .07       0
Bank Sta=31.9,40.9
XS Rating Curve= 0 ,0
Exp/Cntr(USF)=0,0
Exp/Cntr=0.3,0.1

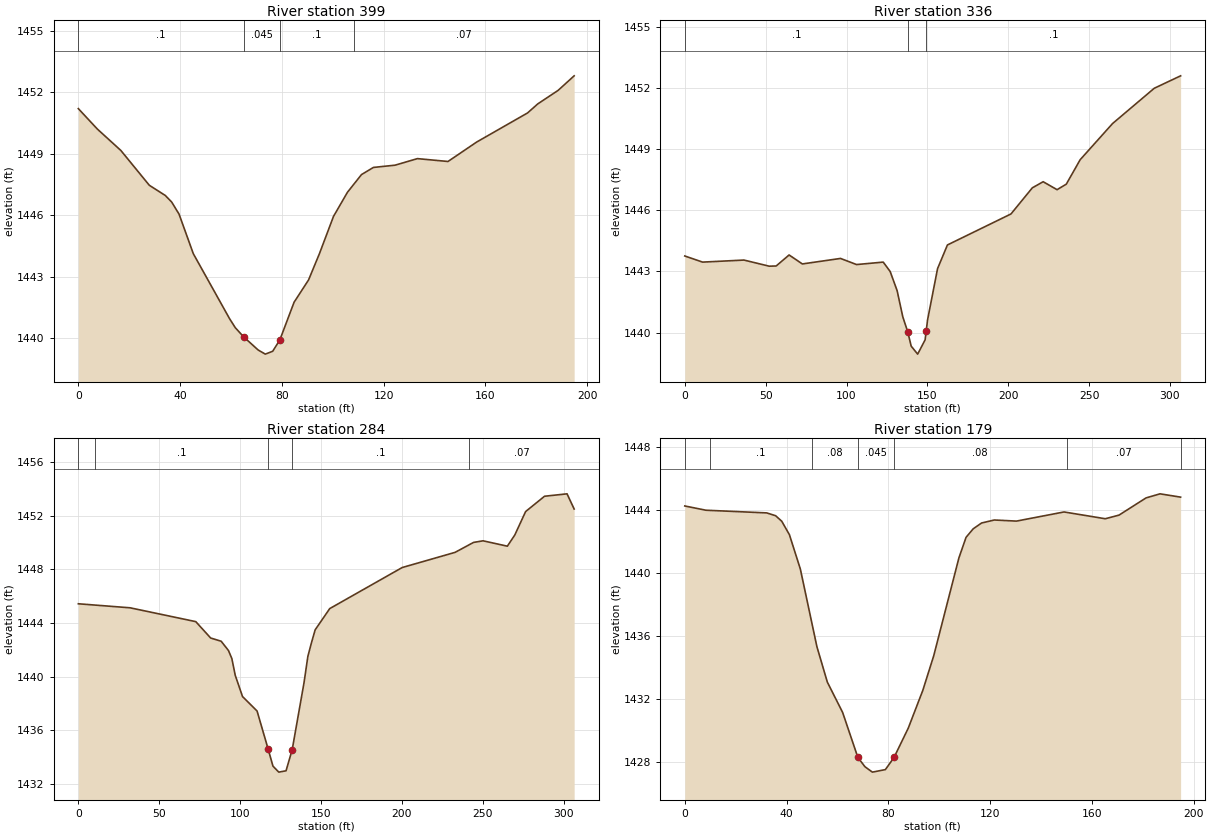
Type RM Length L Ch R = 1 ,399     ,63.1,63.1,63.1
XS GIS Cut Line= 4
2190577.15817196695109.4247202362190600.52271322 695093.49091161
2190680.88594498695008.4721204872190679.11330707694958.855498717
#Sta/Elev= 30
       0  1451.2     7.5  1450.2    16.7 1449.16    27.9 1447.46    34.2 1446.96
    36.7 1446.64    39.6 1446.05    45.2 1444.12    59.4 1440.96    61.7 1440.51
      65 1440.06    70.7 1439.42    73.5 1439.22    76.4 1439.36    79.2 1439.91
    84.8 1441.75    90.5 1442.84    94.8 1444.13   100.3 1445.94   105.8 1447.12
   111.3 1447.98     116 1448.33   124.5 1448.44   133.3 1448.76   145.3 1448.62
   156.6 1449.57   176.6 1450.99   180.6 1451.43   188.6 1452.09   194.9  1452.8
#Mann= 4 ,-1,0
       0      .1       0      65    .045       0    79.2      .1       0
  108.28     .07       0
Bank Sta=65,79.2
XS Rating Curve= 0 ,0
Exp/Cntr(USF)=0,0
Exp/Cntr=0.3,0.1

Type RM Length L Ch R = 1 ,336     ,52.4,52.4,52.4
XS GIS Cut Line= 4
2190693.54417768695235.9110173192190667.75366807695128.450560605
2190698.70227961695052.7983990782190766.61728825694960.812248131
#Sta/Elev= 30
       0 1443.76      11 1443.46    36.6 1443.56    52.2 1443.26    56.5 1443.27
    64.5 1443.81    72.7 1443.37    96.3 1443.64   106.2 1443.34   122.7 1443.46
     127    1443   131.3 1442.06   134.8 1440.78   137.9 1440.03     140 1439.34
     144 1438.95   148.6 1439.65   149.31440.103   150.1 1440.62   156.3 1443.14
   162.4  1444.3   201.7 1445.82   214.9  1447.1   221.6  1447.4   230.2 1447.01
   235.9 1447.28   244.5 1448.48   264.5 1450.25   290.3 1451.98   306.6 1452.59
#Mann= 3 ,-1,0
       0      .1       0   137.9    .045       0   149.3      .1       0
Bank Sta=137.9,149.3
XS Rating Curve= 0 ,0
Exp/Cntr(USF)=0,0
Exp/Cntr=0.3,0.1

Type RM Length L Ch R = 1 ,284     ,104.8,104.8,104.8
XS GIS Cut Line= 5
2190730.51057479695236.7707009732190718.47500364695166.276641369
2190715.89595268695143.0651827182190759.73981902695057.096817347
2190817.33862382694957.373513516
#Sta/Elev= 30
       0 1445.43      32 1445.13    72.6  1444.1    81.8 1442.88    88.3 1442.64
    92.8 1441.95    94.9 1441.35      97  1440.1   101.5 1438.52   110.5 1437.44
   117.3 1434.62   120.3 1433.34   123.9 1432.89   128.4 1432.99   132.2 1434.56
   139.5 1439.54   141.9 1441.52   144.1 1442.52   146.4 1443.49   155.4 1445.07
   200.2 1448.13   232.9 1449.26   244.3    1450   250.2 1450.12   265.2 1449.72
   269.8 1450.55   276.5  1452.3   288.2 1453.44   302.1 1453.62   306.5 1452.49
#Mann= 5 ,-1,0
       0     .08       0      10      .1       0   117.3    .045       0
   132.2      .1       0  241.37     .07       0
Bank Sta=117.3,132.2
XS Rating Curve= 0 ,0
Exp/Cntr(USF)=0,0
Exp/Cntr=0.3,0.1

Type RM Length L Ch R = 1 ,179     ,,,
XS GIS Cut Line= 2
 2190754.5817171695243.6481702032190885.25363246695099.221316379
#Sta/Elev= 30
       0 1444.23     8.3 1443.96    32.2 1443.79    35.7 1443.61    38.1 1443.26
    41.1 1442.41    45.4 1440.23    51.9 1435.31      56 1433.06      62 1431.14
      68 1428.28    70.8 1427.69    73.7 1427.35    78.8 1427.51    82.2 1428.28
    87.8 1430.14    93.5 1432.53    97.8 1434.73   107.7 1440.94   110.5 1442.24
   113.3 1442.78   116.6 1443.15   121.6 1443.34   130.3 1443.27     149 1443.85
   165.2 1443.42   170.6 1443.65   181.2 1444.74   186.7    1445   194.8 1444.79
#Mann= 7 ,-1,0
       0     .08       0      10      .1       0      50     .08       0
      68    .045       0    82.2     .08       0     150     .07       0
  194.77      .1       0
Bank Sta=68,82.2
XS Rating Curve= 0 ,0
Exp/Cntr(USF)=0,0
Exp/Cntr=0.3,0.1
LCMann Table=0

Chan Stop Cuts=-1
Use User Specified Reach Order=0
Composite Channel Slope=5